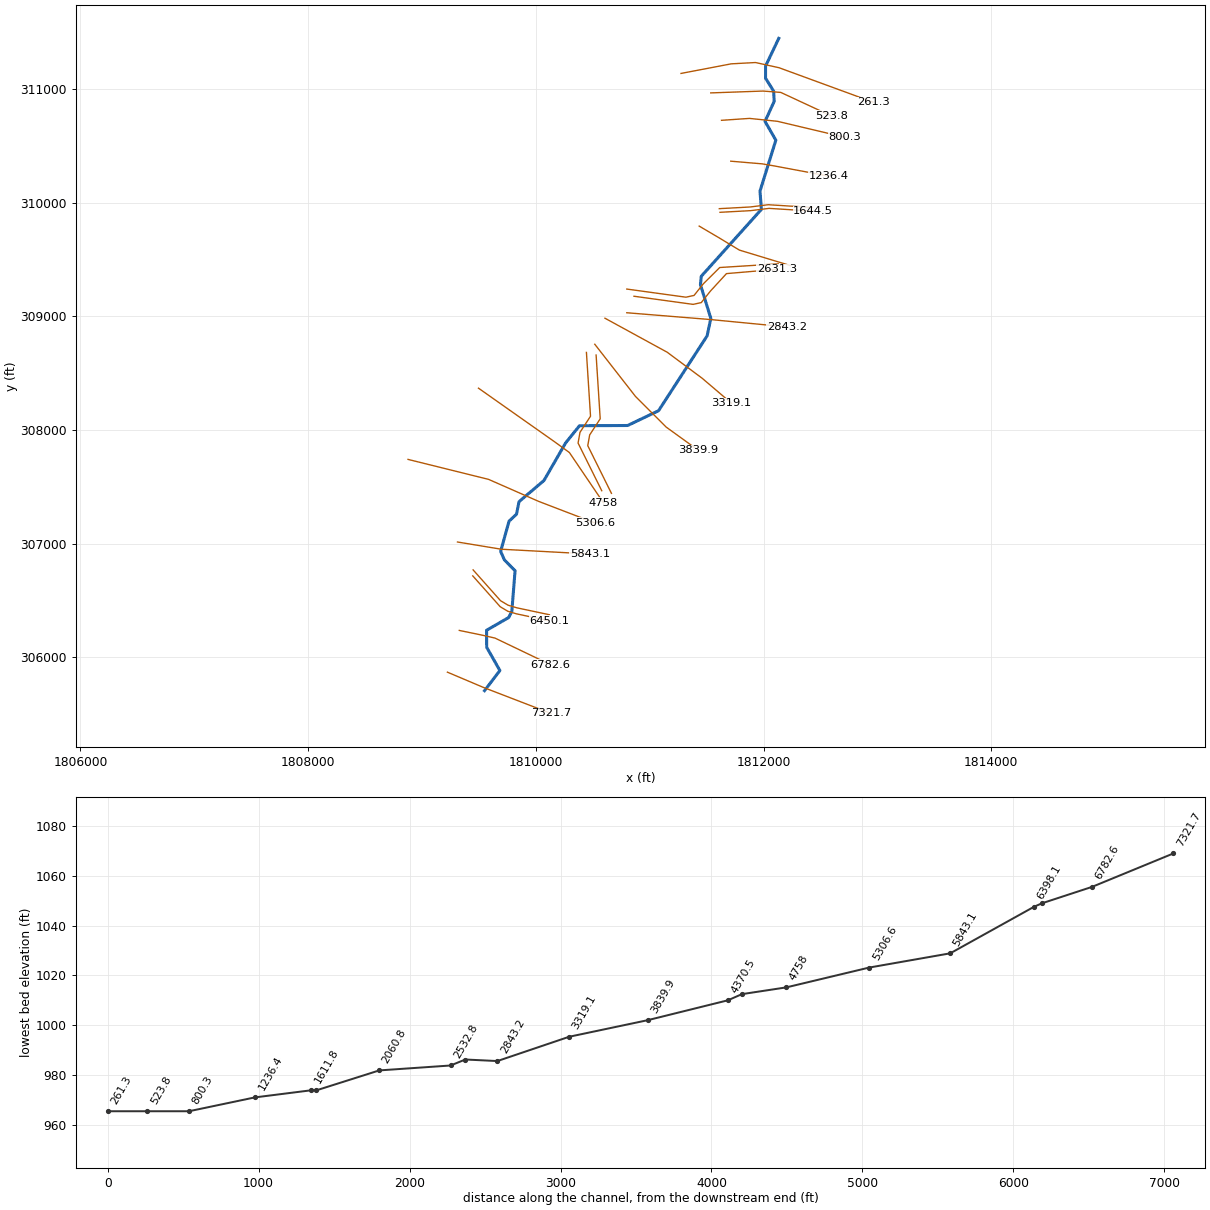
--- OtterCrk.prj (project) ---

Proj Title=OtterCrk
Current Plan=p01
Default Exp/Contr=0,0
English Units
Geom File=g01
Flow File=f01
Plan File=p01
BEGIN DESCRIPTION:
END DESCRIPTION:
DSS Export Rating Curves= 0
DSS Export Rating Curve Sorted= 0
DSS Export Volume Flow Curves= 0
DXF OffsetX= 0
DXF OffsetY= 0
DXF ScaleX= 0
DXF ScaleY= 0

--- OtterCrk.p01 (plan) ---

Plan Title=Floodplain
Program Version=4.00
Geom File=g01
Flow File=f01
K Sum by GR=0
Std Step Tol=0.01
Critical Tol=0.01
Num of Std Step Trials=20
Max Error Tol=0.3
Flow Tol Ratio=0.001
Split Flow NTrial=30
Split Flow Tol=0.02
Split Flow Ratio=0.02
Log Output Level=0
Friction Slope Method=1
Unsteady Friction Slope Method=2
Unsteady Bridges Friction Slope Method=1
Global Log Level=0
CheckData=False
Run HTab=0
Run UNet=0
Run PostProcess=0
UNET Theta=0
UNET Theta Warmup=0
UNET ZTol=0
UNET ZSATol=0
UNET MxIter=0
UNET MaxInSteps=0
UNET DtIC=0
UNET DtMin=0
UNET MaxCRTS=0
UNET WFStab=0
UNET SFStab=0
UNET WFX=0
UNET SFX=0
UNET DSS MLevel=0
UNET DZMax Abort=0
UNET Convert EG Bridges=0
UNET Use Existing IB Tables=0
UNET Froude Limit=0
UNET Froude Power=0
Write IC File=0
Echo Input=False
Echo Output=False
Write Detailed=0

--- OtterCrk.f01 (steady flow) ---

Flow Title=NFF Regression Equation
Program Version=4.10
Number of Profiles= 1
Profile Names=P100yr
River Rch & RM=OtterCrk,Main            ,7321.7
     515
River Rch & RM=OtterCrk,Main            ,5306.6
     563
River Rch & RM=OtterCrk,Main            ,4758
     785
River Rch & RM=OtterCrk,Main            ,3839.9
     790
River Rch & RM=OtterCrk,Main            ,261.3
     877
Boundary for River Rch & Prof#=OtterCrk,Main            , 1
Up Type= 0
Dn Type= 3
Dn Slope=0.01277
DSS Import GetInterval= 0
DSS Import GetPeak= 0
DSS Import FillOption= 0

--- OtterCrk.g01 (geometry) ---

Geom Title=USGS 10m DEM
Program Version=4.10

River Reach=OtterCrk        ,Main
Reach XY= 30
     1809549.526      305706.049     1809684.299      305883.736
     1809568.455      306087.642     1809567.357      306237.727
     1809761.527      306350.058     1809789.407      306405.487
     1809817.657      306761.942     1809724.137      306857.313
     1809690.859      306932.503     1809764.852      307198.106
      1809830.58      307259.915     1809852.657      307370.204
     1810070.929      307555.331     1810261.556      307886.801
     1810383.953      308038.426     1810806.509      308040.382
     1811078.257      308170.651     1811504.917      308829.778
     1811537.134      308983.802     1811445.965      309281.053
     1811453.371      309353.909     1811981.409      309942.832
     1811969.256      310103.599     1812108.425      310551.884
     1812013.431      310717.186      1812093.79      310893.344
     1812089.215      310983.735     1812017.985      311097.261
     1812018.198      311204.103     1812134.213      311448.495

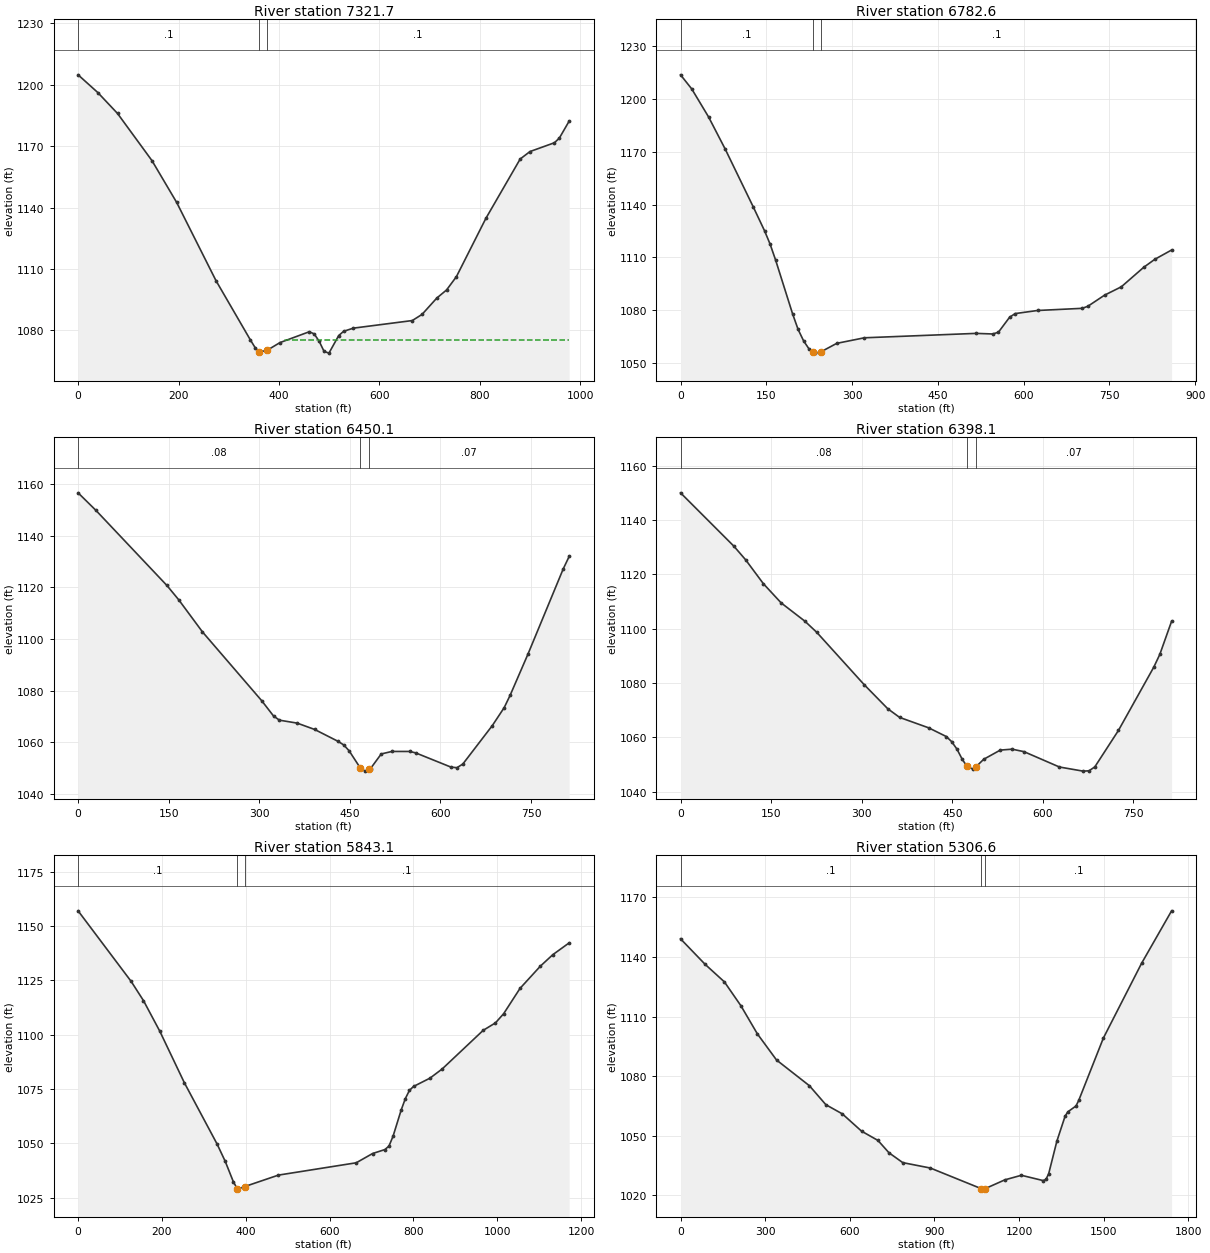
Type RM Length L Ch R = 1 ,7321.7  ,535.7,539.1,542
XS GIS Cut Line= 3
     1809223.278      305869.149     1809539.251       305734.89
     1810131.265      305506.302
#Sta/Elev= 30
       0 1204.77    39.2 1196.13    78.5 1185.92   147.1 1162.89   196.2 1142.53
   274.6  1104.3   343.3 1075.27   353.1 1071.38   360.8 1069.52   375.8 1070.21
   401.9 1074.05   460.5 1079.37   470.2 1078.29     480 1074.74   489.8 1069.78
   499.5 1068.92     519  1077.5   528.8 1079.58   548.3 1081.12   665.5 1084.82
     685 1087.84   714.3  1095.8   733.8 1099.76   753.4 1106.26     812 1134.69
   880.3 1163.66   899.8 1167.31   948.6 1171.62   958.4 1173.91   977.9 1182.19
#Mann= 3 , 0 , 0
       0      .1       0   360.8    .045       0   375.8      .1       0
#XS Ineff= 2 , 0
                          412.65         1075.09
Permanent Ineff=
       F       F
Bank Sta=360.8,375.8
XS Rating Curve= 0 ,0
Exp/Cntr=0.3,0.1

Type RM Length L Ch R = 1 ,6782.6  ,334.1,332.5,330.8
XS GIS Cut Line= 4
     1809327.737      306236.494     1809529.126      306194.827
     1809641.973      306168.786     1810126.348      305936.147
#Sta/Elev= 30
       0  1213.8    19.6 1205.78      49 1189.87    78.3 1171.45   127.3  1138.6
   146.9 1125.12   156.7 1117.46   166.5 1108.21   195.9 1077.92   205.6    1069
   215.3 1062.44     225 1057.75  232.51 1055.96   234.5 1055.51  246.22 1056.37
   273.2 1061.07   321.5 1064.23   516.9 1066.74   546.2  1066.4     556 1067.43
   575.5 1075.93   585.2    1078   624.3 1079.76   702.5 1080.99   712.3 1082.16
   741.6 1088.49   770.9 1093.24     810 1104.31   829.5 1108.89   858.8 1114.16
#Mann= 3 , 0 , 0
       0      .1       0  232.51    .045       0  246.22      .1       0
Bank Sta=232.51,246.22
XS Rating Curve= 0 ,0
Exp/Cntr=0.3,0.1

Type RM Length L Ch R = 1 ,6450.1  ,51.8,52,51.8
XS GIS Cut Line= 5
     1809446.282        306716.4     1809687.167      306445.133
     1809753.425      306405.495     1809829.814      306382.578
     1810116.855      306321.435
#Sta/Elev= 30
       0 1156.51    29.4 1149.76   147.1 1120.69   166.7 1115.14   205.9 1102.76
     304 1076.16   323.6 1070.25   333.4 1068.62   362.8 1067.48   391.7 1065.03
   430.3 1060.46     440 1059.03   448.8 1056.78   467.1 1050.22   475.4 1048.92
   482.1 1049.68   484.3 1049.93     502 1055.56   519.7 1056.53   549.1 1056.52
   558.9 1055.99   617.6 1050.46   627.4 1050.25   637.1 1051.66     686 1066.55
   705.6 1073.47   715.4 1078.22   744.8 1094.06   803.4 1127.12   813.2 1131.93
#Mann= 3 , 0 , 0
       0     .08       0   467.1    .045       0   482.1     .07       0
#XS Ineff= 2 , 0
                             502          1055.5
Permanent Ineff=
       F       F
Bank Sta=467.1,482.1
XS Rating Curve= 0 ,0
Exp/Cntr=0.3,0.1

Type RM Length L Ch R = 1 ,6398.1  ,552.3,555.1,560.2
XS GIS Cut Line= 5
      1809449.06      306769.525     1809689.945      306498.258
     1809756.203       306458.62     1809832.592      306435.703
     1810119.633       306374.56
#Sta/Elev= 30
       0  1150.1    88.2 1130.47   107.8 1125.42   137.3 1116.58   166.7 1109.52
   205.9  1102.8   225.5 1098.71     304 1079.42   343.2 1070.52   362.8 1067.33
     411 1063.48     440 1060.29   448.8 1058.44   457.7 1055.66   466.6 1051.84
   474.4  1049.3   484.3 1048.29   489.4 1049.16     502 1051.89   529.5 1055.28
   549.1 1055.62   568.7 1054.71   627.4 1049.05   666.5 1047.53   676.3 1047.64
     686 1049.08   725.2 1062.54   783.9 1085.94   793.7 1090.57   813.2 1102.78
#Mann= 3 , 0 , 0
       0     .08       0   474.4    .045       0   489.4     .07       0
#XS Ineff= 2 , 0
                          512.38         1052.77
Permanent Ineff=
       F       F
Bank Sta=474.4,489.4
XS Rating Curve= 0 ,0
Exp/Cntr=0.3,0.1

Type RM Length L Ch R = 1 ,5843.1  ,541.8,536.4,527.4
XS GIS Cut Line= 3
     1809311.683      307014.899     1809696.345      306951.339
     1810476.606       306909.32
#Sta/Elev= 30
       0 1156.93   126.7 1124.42     156  1115.6   194.9 1101.53   253.4 1077.85
   331.4 1049.67   350.9 1041.68   370.4 1032.24  379.76 1029.02   380.1 1028.88
   397.8 1030.08   477.8 1035.33   663.4    1041   702.4 1045.26   731.7 1047.08
   741.5 1048.68   751.3 1053.25   770.8 1065.39   780.6 1070.55   790.3 1074.31
   800.1 1076.12   839.2 1079.93   868.5 1084.18   966.2 1101.94   995.5 1105.37
    1015 1109.59  1054.1 1121.25  1102.9 1131.53  1132.2 1136.74  1171.3 1142.19
#Mann= 3 , 0 , 0
       0      .1       0  379.76    .045       0   397.8      .1       0
Bank Sta=379.76,397.8
XS Rating Curve= 0 ,0
Exp/Cntr=0.3,0.1

Type RM Length L Ch R = 1 ,5306.6  ,553.5,548.6,543.7
XS GIS Cut Line= 4
     1808877.655      307741.896      1809585.12      307566.114
     1810023.488      307372.972      1810520.45         307182.
#Sta/Elev= 30
       0 1149.18    87.5 1136.28   155.5 1127.49   213.8 1115.52   272.2 1101.36
   340.2 1088.18   456.8 1075.22   515.1 1065.68   573.5 1061.05   641.5 1052.37
   699.8 1047.68   738.8 1041.47   787.6 1036.52   885.4  1033.8  1065.6 1023.43
  1071.1 1023.18  1080.6 1023.49  1149.4 1027.85    1208 1030.15  1285.4 1027.47
  1295.1 1028.07  1304.8 1030.96  1333.8 1047.34  1362.9 1059.89  1372.6 1062.08
  1401.6 1065.04  1411.3 1067.85  1498.4 1099.16  1633.9 1136.82  1740.4 1163.26
#Mann= 3 , 0 , 0
       0      .1       0  1065.6    .045       0  1080.6      .1       0
Bank Sta=1065.6,1080.6
XS Rating Curve= 0 ,0
Exp/Cntr=0.3,0.1

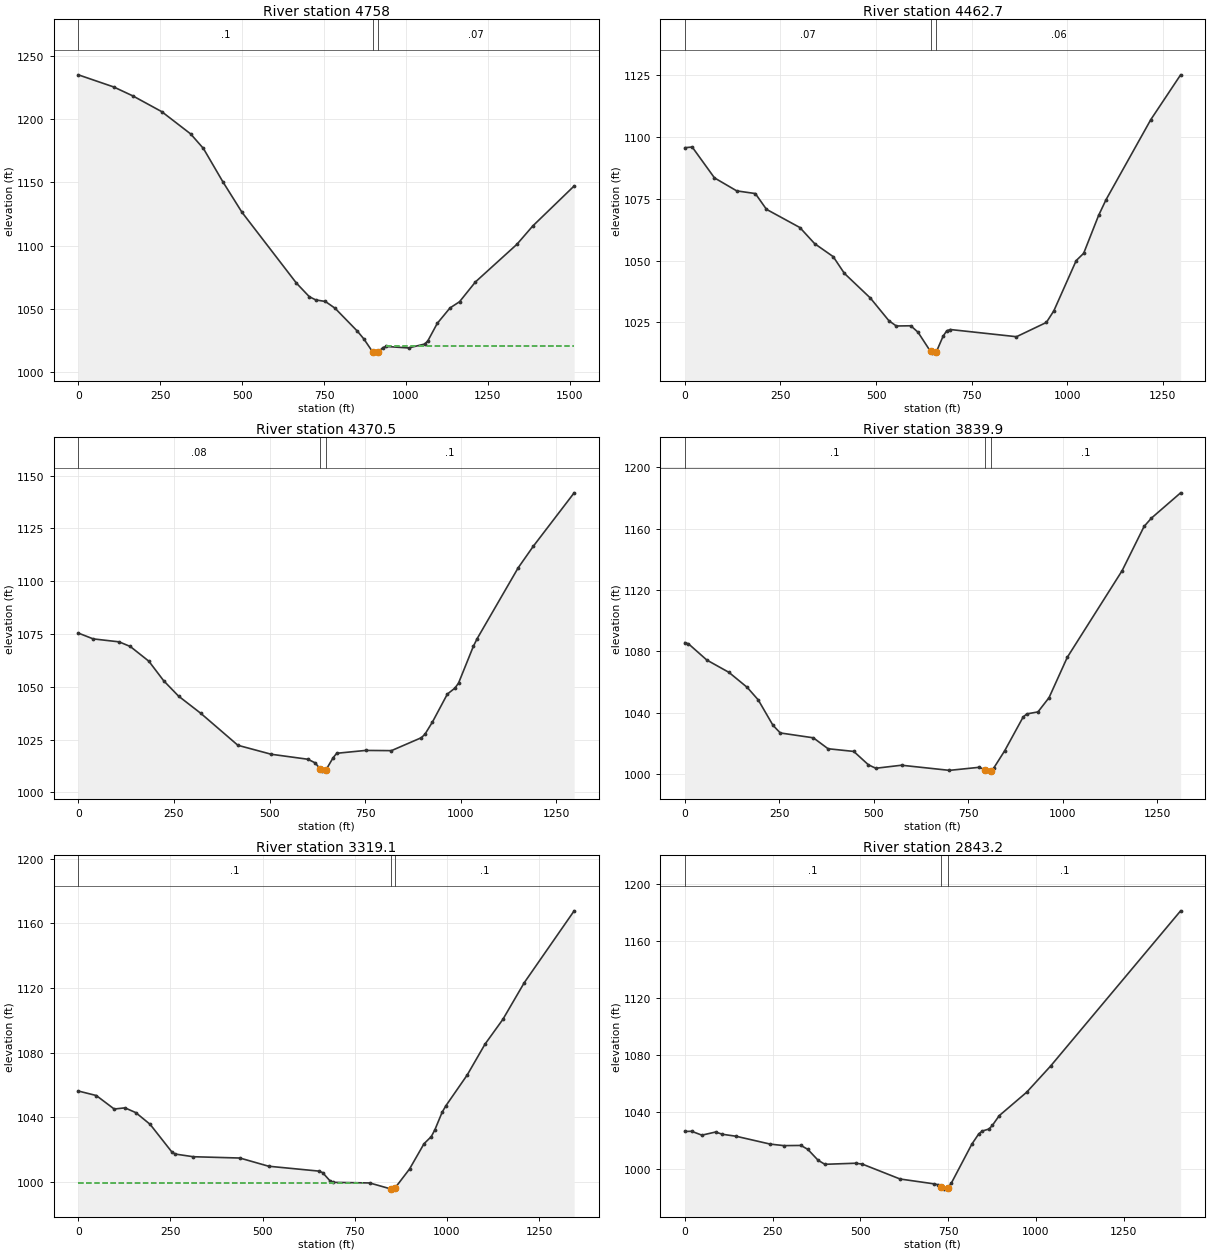
Type RM Length L Ch R = 1 ,4758    ,331.1,295.4,258.8
XS GIS Cut Line= 4
     1809496.144      308369.066     1810160.207      307900.316
     1810294.756      307802.659     1810594.235      307359.951
#Sta/Elev= 30
       0 1234.87   107.7 1225.33   166.5 1218.23   254.6 1205.81   342.8 1188.25
   381.9 1176.74   440.7 1150.67   499.4 1126.45   665.9 1070.45   705.1 1059.78
   724.7 1057.25   754.1    1056   783.5 1050.71     852 1032.53   871.5 1026.48
   898.6 1016.15   910.6 1015.24   913.6 1015.88   930.2 1019.66     940 1020.49
  1008.2 1019.33  1056.8 1022.39  1066.6 1024.75  1095.7 1038.72  1134.6  1050.9
  1163.7  1055.8  1212.3 1071.44  1338.7 1101.08  1387.2 1115.57  1513.6 1147.17
#Mann= 3 , 0 , 0
       0      .1       0   898.6    .045       0   913.6     .07       0
#XS Ineff= 2 , 0
                          939.83         1020.49
Permanent Ineff=
       F       F
Bank Sta=898.6,913.6
XS Rating Curve= 0 ,0
Exp/Cntr=0.3,0.1

Type RM Length L Ch R = 1 ,4462.7  ,91.9,92.2,93.4
XS GIS Cut Line= 5
     1810444.495      308683.736     1810480.563      308122.147
     1810388.072      307980.611     1810371.188      307885.689
     1810579.044      307466.288
#Sta/Elev= 30
       0 1095.73    19.4    1096    77.6  1083.5   135.8 1078.24   184.4 1077.16
   213.5 1070.77   300.8  1063.4   339.6 1056.85   388.1 1051.59   417.2 1044.83
   485.1 1034.84   533.6 1025.65     553 1023.51   590.9  1023.6   609.7 1020.99
   642.4 1013.21   647.3 1012.52   657.4 1012.95   675.5 1019.44   684.9 1021.56
   694.2 1022.08   867.2 1019.17   945.3 1024.95   964.8 1029.64  1023.3 1050.01
  1042.8 1052.95  1081.8 1068.28  1101.3 1074.67  1218.3  1107.1  1296.3 1125.25
#Mann= 3 , 0 , 0
       0     .07       0   642.4    .045       0   657.4     .06       0
Bank Sta=642.4,657.4
XS Rating Curve= 0 ,0
Exp/Cntr=0.3,0.1

Type RM Length L Ch R = 1 ,4370.5  ,499.1,530.6,562.5
XS GIS Cut Line= 5
     1810529.565      308660.819     1810565.632      308099.231
     1810473.141      307957.694     1810456.257      307862.772
     1810664.113      307443.371
#Sta/Elev= 30
       0 1075.42    38.8 1072.67   106.7 1071.26   135.8 1069.07   184.4  1062.1
   223.2 1052.84     262 1045.58   320.2 1037.42   417.2 1022.29   504.5 1018.04
   600.3 1015.68   619.1 1013.97   632.3 1011.13   637.9 1010.06   647.3  1010.6
   666.1 1016.39   675.5 1018.51   751.1 1019.86   818.6 1019.76   896.5 1025.86
   906.2 1027.52   925.8 1033.32   964.8 1046.54   984.3 1049.32     994 1051.72
    1033 1069.25  1042.8 1072.82    1150 1106.34    1189 1116.41  1296.3 1141.82
#Mann= 3 , 0 , 0
       0     .08       0   632.3    .045       0   647.3      .1       0
Bank Sta=632.3,647.3
XS Rating Curve= 0 ,0
Exp/Cntr=0.3,0.1

Type RM Length L Ch R = 1 ,3839.9  ,517.2,520.8,523.5
XS GIS Cut Line= 4
     1810518.027      308755.513       1810876.1      308295.444
     1811145.197      308026.347     1811427.315      307822.353
#Sta/Elev= 30
       0 1085.77     9.7    1085    58.3 1074.43   116.6 1066.44   165.2 1056.62
   194.3 1048.47   233.2 1031.97   252.6 1026.96   340.1 1023.79     379 1016.68
     447 1014.93   485.8  1006.2   505.3 1003.97   573.3 1005.94   700.1  1002.6
   778.2 1004.57     794 1003.13   807.4  1002.1     809 1002.42   817.2 1004.06
   846.5 1015.46   895.2 1037.38     905 1039.36   934.3 1040.66   963.6 1049.94
  1011.9 1076.22    1157 1132.65    1215 1161.41  1234.3 1166.81  1311.7 1183.31
#Mann= 3 , 0 , 0
       0      .1       0     794    .045       0     809      .1       0
#XS Ineff= 2 , 0
          573.76 1005.92
Permanent Ineff=
       F       F
Bank Sta=794,809
XS Rating Curve= 0 ,0
Exp/Cntr=0.3,0.1

Type RM Length L Ch R = 1 ,3319.1  ,463.2,475.9,488
XS GIS Cut Line= 4
     1810607.251      308984.758     1811154.126      308685.279
     1811461.418      308456.112     1811718.982      308236.416
#Sta/Elev= 30
       0 1056.19    48.7  1053.4    97.4 1045.03   126.6 1045.77   155.9 1042.81
   194.8 1035.56   253.3 1018.58     263 1017.16   311.8 1015.51   438.4  1014.7
   516.3 1009.63     653  1006.6   662.8 1005.69   682.5 1000.68   692.3  999.64
   790.6  999.27   847.6  995.58   849.6  995.45   859.4  996.17   898.7 1007.91
     938 1023.56   957.7 1027.98   967.5  1032.2   987.2 1043.07     997 1046.94
  1055.2 1066.12  1103.6 1085.24  1151.9 1100.53    1210 1123.25  1345.4 1167.74
#Mann= 3 , 0 , 0
       0      .1       0   847.6    .045       0   859.4      .1       0
#XS Ineff= 2 , 0
          771.14  999.49
Permanent Ineff=
       F       F
Bank Sta=847.6,859.4
XS Rating Curve= 0 ,0
Exp/Cntr=0.3,0.1

Type RM Length L Ch R = 1 ,2843.2  ,185.6,211.9,235.2
XS GIS Cut Line= 3
     1810799.039      309032.914     1811536.079      308972.907
     1812205.398      308908.141
#Sta/Elev= 30
       0 1026.15    19.5 1026.29    48.6 1023.56    87.6 1025.76     107 1024.19
     146  1022.8   243.2 1017.29   282.2 1016.22   330.8 1016.35   350.3  1013.6
   379.5 1005.99   398.9 1003.12   486.5 1003.88     506 1003.22     613  992.81
   710.3  989.39     720  988.86   729.8   987.1   739.5  985.71   749.2  986.51
     759  989.94   817.4 1017.27   836.9  1024.4   846.7 1026.42   866.2 1027.87
   875.9 1030.45   895.4 1037.25   973.4 1053.66  1041.6 1072.02  1411.9 1180.91
#Mann= 3 , 0 , 0
       0      .1       0   729.8    .045       0   749.2      .1       0
Bank Sta=729.8,749.2
XS Rating Curve= 0 ,0
Exp/Cntr=0.3,0.1

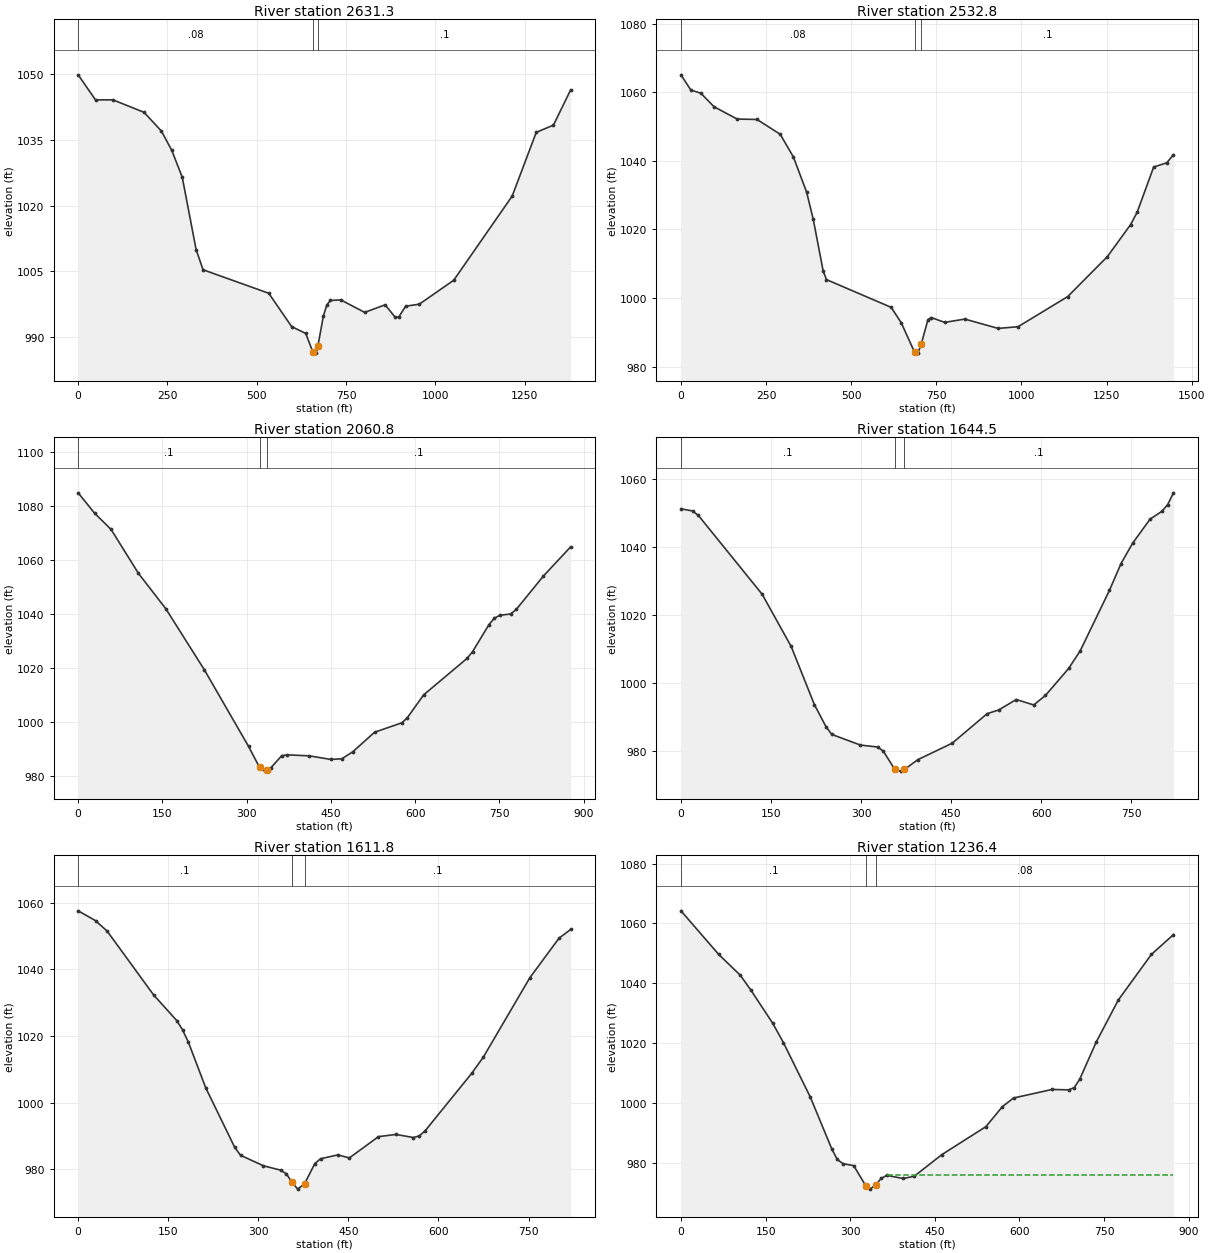
Type RM Length L Ch R = 1 ,2631.3  ,101,98.4,98.7
XS GIS Cut Line= 6
     1810862.211      309178.256     1811381.742      309106.642
     1811453.357      309122.267     1811532.784      309222.527
     1811674.711      309377.475     1812116.117      309415.235
#Sta/Elev= 30
       0 1049.92    48.6 1044.19    97.1 1044.21   184.5 1041.35   233.1 1037.06
   262.2 1032.64   291.4 1026.51   330.2    1010   349.6 1005.38   533.6 1000.01
   597.7  992.39   637.1  990.83   656.8  986.64   666.6  986.33  671.19  987.94
   686.3  994.75   696.1  997.32     706  998.36   735.2   998.5   802.1  995.64
   859.4  997.37     888  994.48   897.6  994.59   916.7  997.05     955  997.51
  1051.4 1002.98  1215.1 1022.22  1282.5 1036.78  1330.6 1038.43  1378.8 1046.49
#Mann= 3 , 0 , 0
       0     .08       0   656.8    .045       0  671.19      .1       0
Bank Sta=656.8,671.19
XS Rating Curve= 0 ,0
Exp/Cntr=0.3,0.1

Type RM Length L Ch R = 1 ,2532.8  ,506.1,472.1,437.5
XS GIS Cut Line= 6
     1810799.016      309241.451     1811318.548      309169.836
     1811390.162      309185.461     1811469.589      309285.722
     1811615.671      309431.095     1812129.572      309463.308
#Sta/Elev= 30
       0  1065.1    29.1 1060.64    58.3 1059.75    97.1 1055.79   165.1  1052.2
   223.4 1052.08   291.4 1047.77   330.2 1041.15     369 1030.91   388.5 1022.98
   417.6 1007.94   427.3 1005.38   617.4  997.28   646.9  992.81   686.3  984.16
   696.1  983.93   706.1  986.73   725.6  993.73   735.5  994.29   774.7   992.9
   833.6  993.86   931.7  991.14     990  991.63  1135.8 1000.41  1252.4 1012.07
  1320.4 1021.38  1339.8 1024.99  1388.4  1038.2  1427.2 1039.45  1446.6 1041.84
#Mann= 3 , 0 , 0
       0     .08       0   686.3    .045       0   706.1      .1       0
Bank Sta=686.3,706.1
XS Rating Curve= 0 ,0
Exp/Cntr=0.3,0.1

Type RM Length L Ch R = 1 ,2060.8  ,399.9,416.2,431.3
XS GIS Cut Line= 4
      1811434.87      309795.708     1811603.096      309696.485
     1811787.992      309584.506     1812233.304       309449.09
#Sta/Elev= 30
       0 1084.78    29.3 1077.24    58.6 1071.26   107.4 1055.01   156.2 1041.91
   224.8 1019.36   303.4  991.08     323  983.34   332.9  981.96   335.6  982.27
   342.7   983.1   362.3  987.64   372.2  987.98   411.5   987.6   450.3  986.27
   469.6  986.53     489  989.11   527.8  996.34   576.3   999.8     586 1001.66
   615.1 1010.13   692.7 1023.66   702.4 1026.15   731.5 1036.11   741.2  1038.5
   750.9 1039.53   770.2 1040.04     780 1041.69   828.4 1054.05   876.9 1064.83
#Mann= 3 , 0 , 0
       0      .1       0     323    .045       0   335.6      .1       0
#XS Ineff= 2 , 0
                          371.78          987.95
Permanent Ineff=
       F       F
Bank Sta=323,335.6
XS Rating Curve= 0 ,0
Exp/Cntr=0.3,0.1

Type RM Length L Ch R = 1 ,1644.5  ,33.5,32.7,32.7
XS GIS Cut Line= 4
     1811617.791      309916.997     1811887.756      309931.754
     1812048.346      309951.719     1812435.499      309927.413
#Sta/Elev= 30
       0 1051.11    19.3 1050.49      29 1049.17   135.2 1025.99   183.5 1010.65
   222.1  993.57   241.4  987.08   251.1  984.78   298.9  981.64   327.5  981.07
     337  979.85     356  974.48   365.6  973.98   372.2  974.47   394.1  977.32
   451.6  982.19   509.8  990.87   529.2  991.98   558.3  995.04   587.4  993.44
   606.8  996.22   645.6 1004.18   664.9  1009.4   713.4 1027.11   732.8 1035.03
   752.2 1041.04   781.3 1048.12   800.7 1050.36   810.4 1052.35   820.1 1055.82
#Mann= 3 , 0 , 0
       0      .1       0     356    .045       0   372.2      .1       0
Bank Sta=356,372.2
XS Rating Curve= 0 ,0
Exp/Cntr=0.3,0.1

Type RM Length L Ch R = 1 ,1611.8  ,381.6,375.3,368.7
XS GIS Cut Line= 4
     1811611.714      309949.115      1811881.68      309963.872
      1812042.27      309983.837     1812429.423      309959.532
#Sta/Elev= 30
       0 1057.52      29 1054.57    48.3 1051.43   125.5 1032.32   164.2 1024.58
   173.8 1021.81   183.5 1018.12   212.4 1004.43   260.7  986.54   270.4  984.17
   308.4  981.02     337  979.71   346.5  978.63     356   976.1   365.6  974.01
     377  975.63   394.1  981.69   403.6  983.12   432.2  984.28   451.6  983.38
   500.1  989.76   529.2  990.42   558.3  989.49     568  989.98   577.7   991.5
   655.2 1008.73   674.6  1013.6   752.2 1037.46   800.7 1049.31   820.1 1051.93
#Mann= 3 , 0 , 0
       0      .1       0     356    .045       0     377      .1       0
Bank Sta=356,377
XS Rating Curve= 0 ,0
Exp/Cntr=0.3,0.1

Type RM Length L Ch R = 1 ,1236.4  ,434.5,436.1,436.5
XS GIS Cut Line= 4
     1811712.561      310367.062     1811988.603      310343.624
     1812094.071      310325.395      1812574.54      310235.552
#Sta/Elev= 30
       0 1064.22    66.9 1049.63   105.1  1042.7   124.2 1037.62   162.4 1026.68
   181.5 1020.18   229.3  1001.9   267.5   984.5     277  981.09   286.8  979.67
   306.2  978.99   328.1  972.07   335.4  971.14   345.2  972.63   354.9  974.72
   364.6  975.74   393.8   974.7   413.4  975.44   462.3  982.67   540.5  992.05
   569.8  998.75   589.4 1001.61   657.8 1004.48   687.1 1004.34   696.9 1005.09
   706.7 1007.88     736 1020.34   775.1 1034.38   833.8 1049.65   872.9 1056.27
#Mann= 3 , 0 , 0
       0      .1       0   328.1    .045       0   345.2     .08       0
#XS Ineff= 2 , 0
                           364.5          975.73
Permanent Ineff=
       F       F
Bank Sta=328.1,345.2
XS Rating Curve= 0 ,0
Exp/Cntr=0.3,0.1

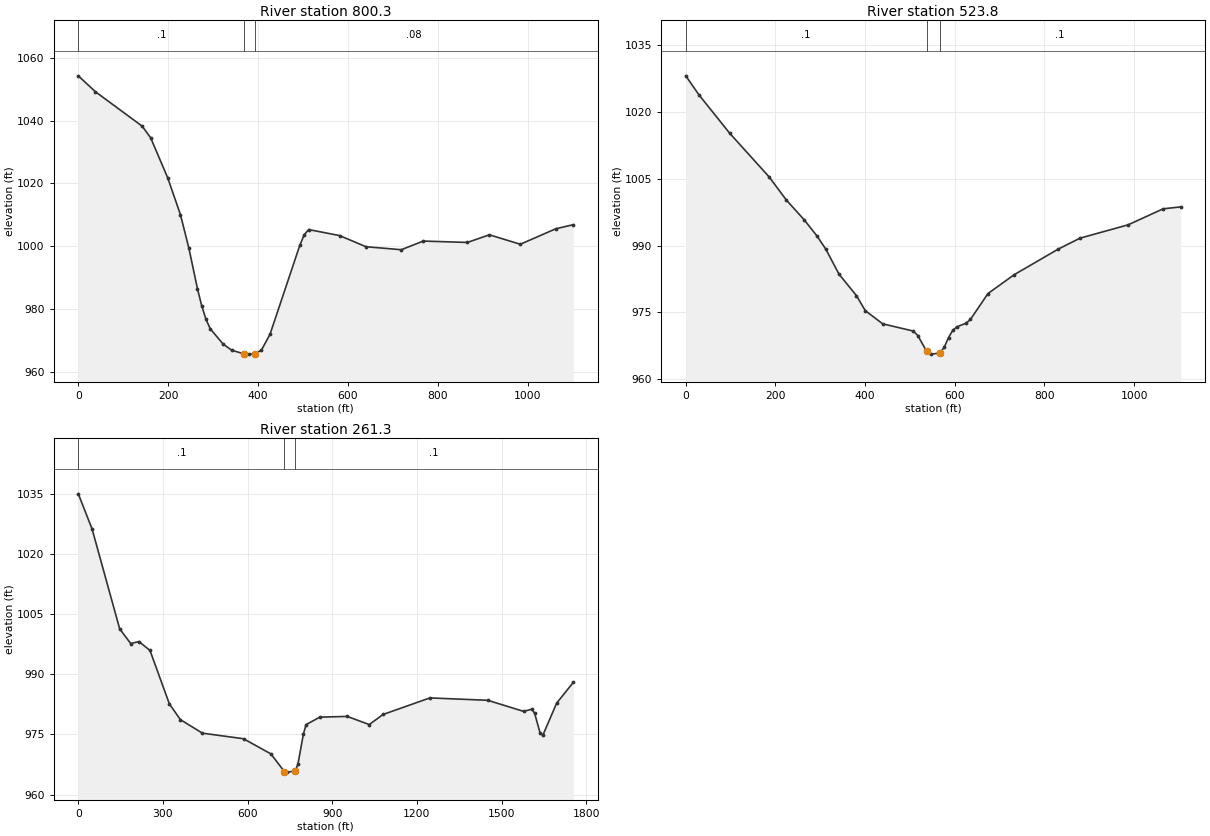
Type RM Length L Ch R = 1 ,800.3   ,277.6,276.5,276.3
XS GIS Cut Line= 4
     1811631.039      310726.802     1811876.782      310743.742
     1812122.358      310718.121     1812714.372      310577.496
#Sta/Elev= 30
       0 1054.26    37.9 1049.22   142.1 1038.24   161.1 1034.52     199 1021.79
   227.4 1010.04   246.3  999.29   265.3  986.41   274.8  980.96   284.3  976.68
   293.8  973.66   322.3  968.83   341.3  966.86   369.8  965.64   379.3   965.6
   392.3   965.6   407.8   966.9   426.8  971.93   493.2 1000.29     503 1003.66
   512.9 1005.28   581.6 1003.37   640.4  999.82     719  998.86     768 1001.62
   866.2 1001.18   915.2 1003.61     984  1000.6  1062.5 1005.51  1101.7 1006.84
#Mann= 3 , 0 , 0
       0      .1       0   369.8    .045       0   392.3     .08       0
Bank Sta=369.8,392.3
XS Rating Curve= 0 ,0
Exp/Cntr=0.3,0.1

Type RM Length L Ch R = 1 ,523.8   ,264.8,262.5,259.3
XS GIS Cut Line= 4
      1811536.84      310968.121     1811995.391      310984.397
     1812151.641      310972.461     1812594.349      310766.298
#Sta/Elev= 30
       0 1028.17    29.3 1023.91    97.6 1015.31   185.5  1005.5   224.5 1000.23
   263.6  995.86   292.9  992.14   312.4   989.2   341.7   983.6   380.7  978.76
   400.3  975.39   439.3  972.41   507.8  970.78   517.6  969.77   537.2  966.25
     547   965.6   566.6  965.83   576.4  967.12   586.2  969.33     596  971.02
   605.8  971.78   625.3  972.55   635.1  973.42   674.2  979.23   732.8  983.47
   830.4  989.19   879.3  991.67   986.7  994.67  1064.8  998.27  1103.9   998.7
#Mann= 3 , 0 , 0
       0      .1       0   537.2    .045       0   566.6      .1       0
Bank Sta=537.2,566.6
XS Rating Curve= 0 ,0
Exp/Cntr=0.3,0.1

Type RM Length L Ch R = 1 ,261.3   ,266.1,261.3,256.4
XS GIS Cut Line= 5
     1811275.313      311139.487     1811717.104      311224.037
     1811930.125      311235.496     1812136.895      311189.662
     1812962.118      310886.709
#Sta/Elev= 30
       0 1035.04    48.9 1026.27   146.7 1001.35   185.8  997.68   215.1  998.18
   254.2  995.95   322.7  982.65   361.8   978.7     440  975.32   585.6  973.93
   682.4  970.16   730.5  965.73   740.2   965.6     769  965.86   778.7  967.66
   797.9  975.13   807.5  977.46   855.7  979.32   953.1   979.5  1031.2  977.47
    1080  979.98  1246.1  984.12  1451.2  983.52  1578.2  980.76  1607.5   981.3
  1617.3  980.29  1636.8  975.32  1646.6  974.83  1695.4  982.81    1754  987.97
#Mann= 3 , 0 , 0
       0      .1       0   730.5    .045       0     769      .1       0
Bank Sta=730.5,769
XS Rating Curve= 0 ,0
Exp/Cntr=0.3,0.1

Chan Stop Cuts=-1
Use User Specified Reach Order=0
Composite Channel Slope=5